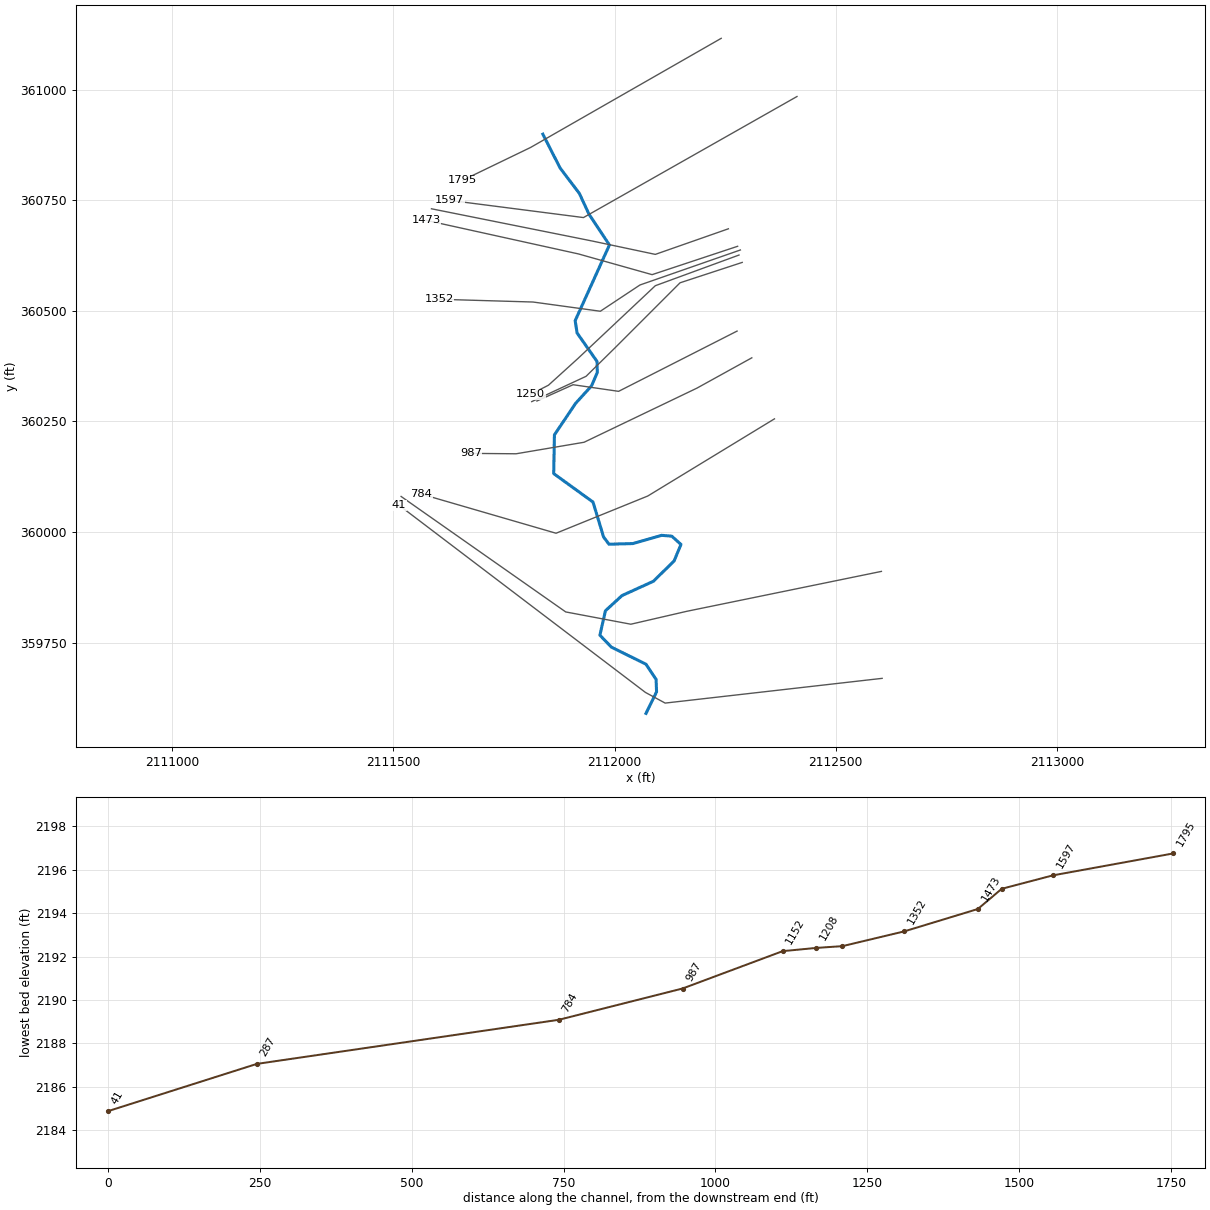
--- SNKNGCKT4.prj (project) ---

Proj Title=SNKNGCKT4
Current Plan=p01
Default Exp/Contr=0.3,0.1
English Units
Geom File=g01
Flow File=f01
Plan File=p01
Y Axis Title=Elevation
X Axis Title(PF)=Main Channel Distance
X Axis Title(XS)=Station
BEGIN DESCRIPTION:
Stream Name- Sinking Creek Tributary 4
Flood Zone: Zone A
Greenbrier County, WV
County-Wide Study
WVDHSEM-2018-3, Flood Risk Project
HEC-RAS Version: 5.0.7
General Notes:
For the Hydrology Regression was used.
END DESCRIPTION:
DSS Export Rating Curves= 0
DSS Export Rating Curve Sorted= 0
DSS Export Volume Flow Curves= 0
DXF Filename=SNKNGCKT4.F2.
DXF OffsetX= 0
DXF OffsetY= 0
DXF ScaleX= 1
DXF ScaleY= 10

--- SNKNGCKT4.p01 (plan) ---

Plan Title=Floodplain
Program Version=5.07
Short Identifier=Floodplain
Geom File=g01
Flow File=f01
Subcritical Flow
K Sum by GR= 0
Std Step Tol= 0.01
Critical Tol= 0.01
Num of Std Step Trials= 20
Max Error Tol= 0.3
Flow Tol Ratio= 0.001
Split Flow NTrial= 30
Split Flow Tol= 0.02
Split Flow Ratio= 0.02
Log Output Level= 0
Friction Slope Method= 1
Unsteady Friction Slope Method= 2
Unsteady Bridges Friction Slope Method= 1
Parabolic Critical Depth
Global Vel Dist= 0 , 0 , 0
Global Log Level= 0
CheckData=True
Encroach Param=-1 ,0,0, 0
Computation Interval=1MIN
Output Interval=1HOUR
Instantaneous Interval=1HOUR
Mapping Interval=1HOUR
Computation Time Step Use Courant=        0
Computation Time Step Use Time Series=    0
Computation Time Step Count To Double=0
Computation Time Step Max Doubling=0
Computation Time Step Max Halving=0
Computation Time Step Residence Courant=0
Run HTab= 0
Run UNet= 0
Run Sediment= 0
Run PostProcess= 0
Run WQNet= 0
Run RASMapper= 0
UNET Theta= 1
UNET Theta Warmup= 1
UNET ZTol= 0.02
UNET ZSATol= 0.02
UNET MxIter= 20
UNET Max Iter WO Improvement= 0
UNET MaxInSteps= 0
UNET DtIC= 0
UNET DtMin= 0
UNET MaxCRTS= 20
UNET WFStab= 2
UNET SFStab= 1
UNET WFX= 1
UNET SFX= 1
UNET 1D Methodology=Finite Difference
UNET DSS MLevel= 4
UNET Pardiso=0
UNET DZMax Abort= 100
UNET Use Existing IB Tables=-1
UNET Froude Reduction=False
UNET Froude Limit= 0.8
UNET Froude Power= 4
UNET D1 Cores= 0
UNET D2 Coriolis=0
UNET D2 Cores= 0
UNET D2 Theta= 1
UNET D2 Theta Warmup= 1
UNET D2 Z Tol= 0.01
UNET D2 Volume Tol= 0.01
UNET D2 Max Iterations= 20
UNET D2 Equation= 0
UNET D2 RampUpFraction=0.1
UNET D2 TimeSlices= 1
UNET D2 BCVolumeCheck=0
UNET D1D2 MaxIter= 0
UNET D1D2 ZTol=0.01
UNET D1D2 QTol=0.1
UNET D1D2 MinQTol=1
Write IC File= 0
Write IC File at Fixed DateTime=0
Write IC File at Sim End=0
Echo Input=False
Echo Parameters=False
Echo Output=False
Write Detailed= 0
HDF Write Warmup=0
HDF Write Time Slices=0
HDF Flush=0
HDF Face Node Velocities=0
HDF Compression= 1
HDF Chunk Size= 1
HDF Spatial Parts= 1
HDF Use Max Rows=0
HDF Fixed Rows= 1
Calibration Method= 0
Calibration Iterations= 20
Calibration Max Change=0.05
Calibration Tolerance=0.2
Calibration Maximum=1.5
Calibration Minimum=0.5
Calibration Optimization Method= 1
WQ AD Non Conservative
WQ ULTIMATE=-1
WQ Max Comp Step=1HOUR
WQ Output Interval=15MIN
WQ Output Selected Increments= 0
WQ Output face flow=0
WQ Output face velocity=0
WQ Output face area=0
WQ Output face dispersion=0
WQ Output cell volume=0
WQ Output cell surface area=0
WQ Output cell continuity=0
WQ Output cumulative cell continuity=0
WQ Output face conc=0
WQ Output face dconc_dx=0
WQ Output face courant=0
WQ Output face peclet=0
WQ Output face adv mass=0
WQ Output face disp mass=0
WQ Output cell mass=0
WQ Output cell source sink temp=0
WQ Output nsm pathways=0
WQ Output nsm derived pathways=0
WQ Output MaxMinRange=-1
WQ Daily Max Min Mean=-1
WQ Daily Range=0
WQ Daily Time=0
WQ Create Restart=0
WQ Fixed Restart=0
WQ System Summary=0
WQ Write To DSS=0
WQ Use Fixed Temperature=0
Sorting and Armoring Iterations= 10
XS Update Threshold= 0.02
Bed Roughness Predictor= 0
Hydraulics Update Threshold= 0.02
Energy Slope Method= 1
Volume Change Method= 1
Sediment Retention Method= 0
XS Weighting Method= 0
Number of US Weighted Cross Sections= 1
Number of DS Weighted Cross Sections= 1
Upstream XS Weight=0
Main XS Weight=1
Downstream XS Weight=0
Number of DS XS's Weighted with US Boundary= 1
Upstream Boundary Weight= 1
Weight of XSs Associated with US Boundary= 0
Number of US XS's Weighted with DS Boundary= 1
Downstream Boundary Weight= 0.5
Weight of XSs Associated with DS Boundary= 0.5
Percentile Method= 0
Sediment Output Level= 3
Mass or Volume Output= 0
Output Increment Type= 1
Profile and TS Output Increment= 1
XS Output Flag= 0
XS Output Increment= 10
Write Gradation File= 0
Read Gradation Hotstart= 0
Write HDF5 File= 1
Write Binary Output= 1
Write DSS Sediment File= 0
SV Curve= 0
Specific Gage Flag= 0

--- SNKNGCKT4.f01 (steady flow) ---

Flow Title=Flow
Program Version=5.07
Number of Profiles= 6
Profile Names=f1p,f10p,f4p,f2p,f02p,f1pplus
River Rch & RM=SNKNGCKT4,Main            ,1795
      33    15.6    21.9    27.3    48.7    48.8
River Rch & RM=SNKNGCKT4,Main            ,1152
    39.5    18.8    26.3    32.7      58    58.4
Boundary for River Rch & Prof#=FLYNNCK,Main            , 1
Up Type= 0
Dn Type= 3
Dn Slope=0.009659
Boundary for River Rch & Prof#=FLYNNCK,Main            , 2
Up Type= 0
Dn Type= 3
Dn Slope=0.009659
Boundary for River Rch & Prof#=FLYNNCK,Main            , 3
Up Type= 0
Dn Type= 3
Dn Slope=0.009659
Boundary for River Rch & Prof#=FLYNNCK,Main            , 4
Up Type= 0
Dn Type= 3
Dn Slope=0.009659
Boundary for River Rch & Prof#=FLYNNCK,Main            , 5
Up Type= 0
Dn Type= 3
Dn Slope=0.009659
Boundary for River Rch & Prof#=FLYNNCK,Main            , 6
Up Type= 0
Dn Type= 3
Dn Slope=0.009659
Boundary for River Rch & Prof#=HUGHRTCK,Main            , 1
Up Type= 0
Dn Type= 3
Dn Slope=0.002151
Boundary for River Rch & Prof#=HUGHRTCK,Main            , 2
Up Type= 0
Dn Type= 3
Dn Slope=0.002151
Boundary for River Rch & Prof#=HUGHRTCK,Main            , 3
Up Type= 0
Dn Type= 3
Dn Slope=0.002151
Boundary for River Rch & Prof#=HUGHRTCK,Main            , 4
Up Type= 0
Dn Type= 3
Dn Slope=0.002151
Boundary for River Rch & Prof#=HUGHRTCK,Main            , 5
Up Type= 0
Dn Type= 3
Dn Slope=0.002151
Boundary for River Rch & Prof#=HUGHRTCK,Main            , 6
Up Type= 0
Dn Type= 3
Dn Slope=0.002151
Boundary for River Rch & Prof#=HUGHRTCKT1,Main            , 1
Up Type= 0
Dn Type= 3
Dn Slope=0.008324
Boundary for River Rch & Prof#=HUGHRTCKT1,Main            , 2
Up Type= 0
Dn Type= 3
Dn Slope=0.008324
Boundary for River Rch & Prof#=HUGHRTCKT1,Main            , 3
Up Type= 0
Dn Type= 3
Dn Slope=0.008324
Boundary for River Rch & Prof#=HUGHRTCKT1,Main            , 4
Up Type= 0
Dn Type= 3
Dn Slope=0.008324
Boundary for River Rch & Prof#=HUGHRTCKT1,Main            , 5
Up Type= 0
Dn Type= 3
Dn Slope=0.008324
Boundary for River Rch & Prof#=HUGHRTCKT1,Main            , 6
Up Type= 0
Dn Type= 3
Dn Slope=0.008324
Boundary for River Rch & Prof#=SNKNGCKT1,Main            , 1
Up Type= 0
Dn Type= 3
Dn Slope=0.003593
Boundary for River Rch & Prof#=SNKNGCKT1,Main            , 2
Up Type= 0
Dn Type= 3
Dn Slope=0.003593
Boundary for River Rch & Prof#=SNKNGCKT1,Main            , 3
Up Type= 0
Dn Type= 3
Dn Slope=0.003593
Boundary for River Rch & Prof#=SNKNGCKT1,Main            , 4
Up Type= 0
Dn Type= 3
Dn Slope=0.003593
Boundary for River Rch & Prof#=SNKNGCKT1,Main            , 5
Up Type= 0
Dn Type= 3
Dn Slope=0.003593
Boundary for River Rch & Prof#=SNKNGCKT1,Main            , 6
Up Type= 0
Dn Type= 3
Dn Slope=0.003593
Boundary for River Rch & Prof#=SNKNGCKT2,Main            , 1
Up Type= 0
Dn Type= 3
Dn Slope=0.006517
Boundary for River Rch & Prof#=SNKNGCKT2,Main            , 2
Up Type= 0
Dn Type= 3
Dn Slope=0.006517
Boundary for River Rch & Prof#=SNKNGCKT2,Main            , 3
Up Type= 0
Dn Type= 3
Dn Slope=0.006517
Boundary for River Rch & Prof#=SNKNGCKT2,Main            , 4
Up Type= 0
Dn Type= 3
Dn Slope=0.006517
Boundary for River Rch & Prof#=SNKNGCKT2,Main            , 5
Up Type= 0
Dn Type= 3
Dn Slope=0.006517
Boundary for River Rch & Prof#=SNKNGCKT2,Main            , 6
Up Type= 0
Dn Type= 3
Dn Slope=0.006517
Boundary for River Rch & Prof#=SNKNGCKT3,Main            , 1
Up Type= 0
Dn Type= 3
Dn Slope=0.00548
Boundary for River Rch & Prof#=SNKNGCKT3,Main            , 2
Up Type= 0
Dn Type= 3
Dn Slope=0.00548
Boundary for River Rch & Prof#=SNKNGCKT3,Main            , 3
Up Type= 0
Dn Type= 3
Dn Slope=0.00548
Boundary for River Rch & Prof#=SNKNGCKT3,Main            , 4
Up Type= 0
Dn Type= 3
Dn Slope=0.00548
Boundary for River Rch & Prof#=SNKNGCKT3,Main            , 5
Up Type= 0
Dn Type= 3
Dn Slope=0.00548
Boundary for River Rch & Prof#=SNKNGCKT3,Main            , 6
Up Type= 0
Dn Type= 3
Dn Slope=0.00548
Boundary for River Rch & Prof#=SNKNGCKT4,Main            , 1
Up Type= 0
Dn Type= 3
Dn Slope=0.00461
Boundary for River Rch & Prof#=SNKNGCKT4,Main            , 2
Up Type= 0
Dn Type= 3
Dn Slope=0.00461
Boundary for River Rch & Prof#=SNKNGCKT4,Main            , 3
Up Type= 0
Dn Type= 3
Dn Slope=0.00461
Boundary for River Rch & Prof#=SNKNGCKT4,Main            , 4
Up Type= 0
Dn Type= 3
Dn Slope=0.00461
Boundary for River Rch & Prof#=SNKNGCKT4,Main            , 5
Up Type= 0
Dn Type= 3
Dn Slope=0.00461
Boundary for River Rch & Prof#=SNKNGCKT4,Main            , 6
Up Type= 0
Dn Type= 3
Dn Slope=0.00461
Boundary for River Rch & Prof#=STONYRN,Main            , 1
Up Type= 0
Dn Type= 3
Dn Slope=0.005293
Boundary for River Rch & Prof#=STONYRN,Main            , 2
Up Type= 0
Dn Type= 3
Dn Slope=0.005293
Boundary for River Rch & Prof#=STONYRN,Main            , 3
Up Type= 0
Dn Type= 3
Dn Slope=0.005293
Boundary for River Rch & Prof#=STONYRN,Main            , 4
Up Type= 0
Dn Type= 3
Dn Slope=0.005293
Boundary for River Rch & Prof#=STONYRN,Main            , 5
Up Type= 0
Dn Type= 3
Dn Slope=0.005293
Boundary for River Rch & Prof#=STONYRN,Main            , 6
Up Type= 0
Dn Type= 3
Dn Slope=0.005293
DSS Import GetInterval= 0
DSS Import GetPeak= 0
DSS Import FillOption= 0

--- SNKNGCKT4.g01 (geometry) ---

Geom Title=Geometry
Program Version=5.07

River Reach=SNKNGCKT4       ,Main
Reach XY= 30
2111837.74703614360899.4957833142111876.88442506360822.841409057
2111920.23900019360765.6581517242111942.06700871360718.643979531
2111988.29201064360648.8745653932111910.82169314360477.663621724
 2111915.2554113360449.821485817 2111960.2583222360385.586732378
2111960.93970314360360.7409553082111947.86689463360330.376186639
2111911.56480189360290.5324343142111863.92868715360219.489708486
2111862.32249195360131.9520700232111951.14805606360067.615885392
2111975.16780322359988.4649315062111987.28587402359972.307503785
2112041.26637117359973.7763608512112106.48665614359992.355209142
2112129.27302788359990.5323781372112150.10631955359971.782415643
2112134.48135081359934.2824906412112087.60644455359888.449248984
2112016.77325289359856.1576468942111979.27299981359821.782387555
 2111966.7730248359766.5741646442111992.81463939359739.490885481
2112070.93981121359700.9492958932112093.85643205359666.574036554
2112094.89809664359638.4490928052112071.01198955359589.767759725

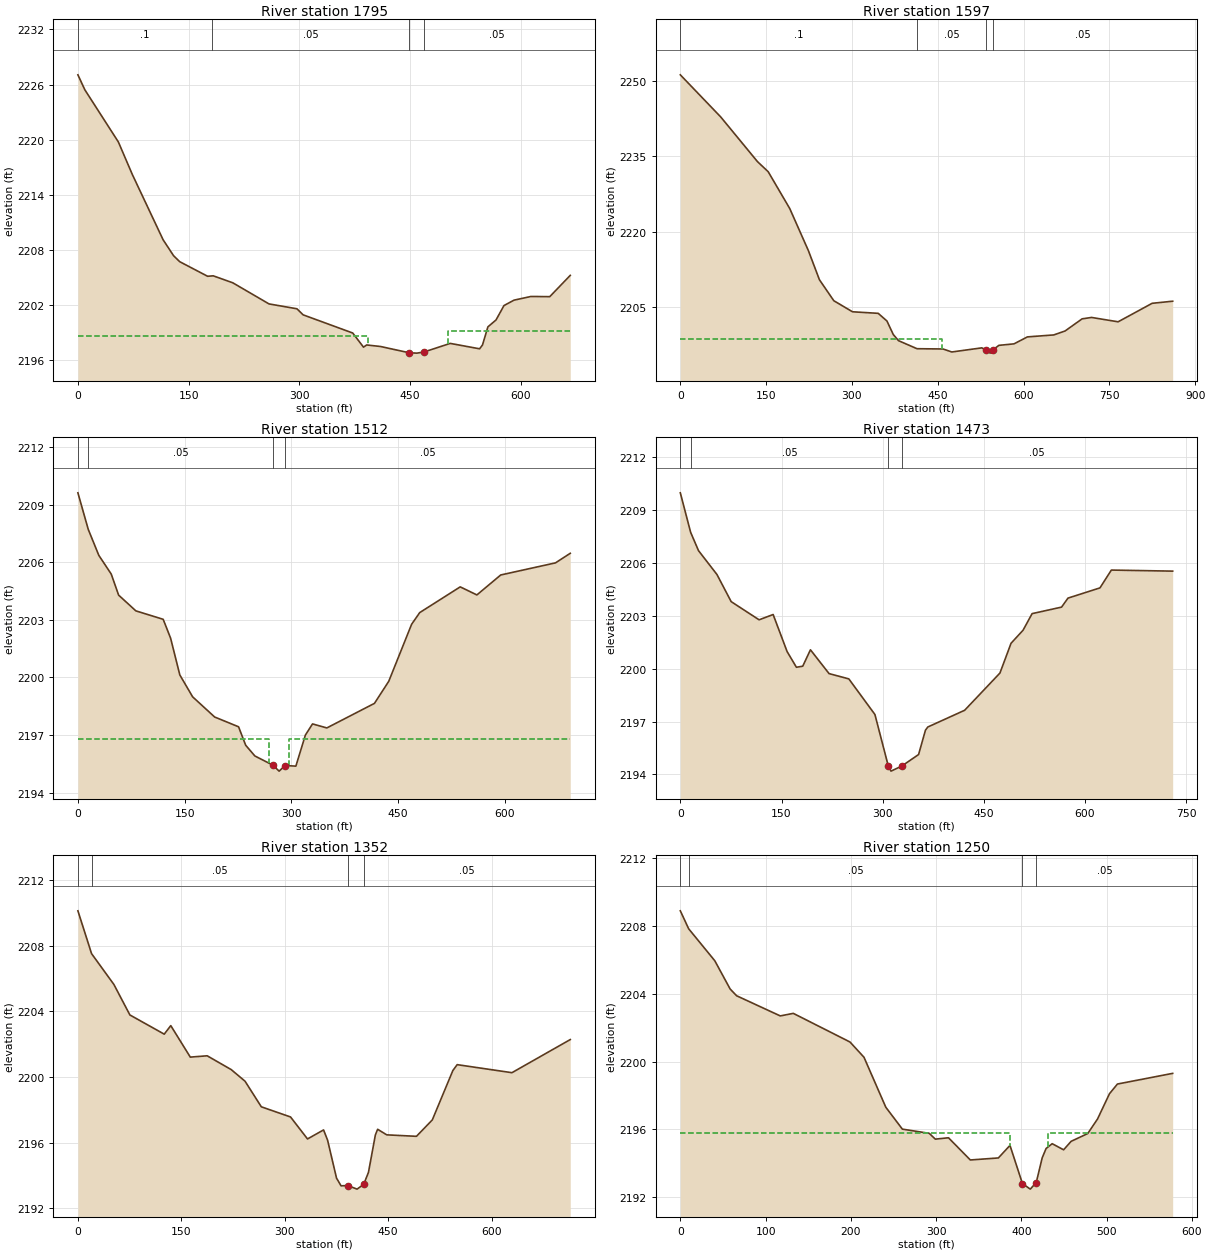
Type RM Length L Ch R = 1 ,1795    ,202.3,198.2,201.7
XS GIS Cut Line= 3
2112241.07004839361116.2355073092111809.81992663360869.360672981
 2111656.6949048360795.402159482
#Sta/Elev= 30
       0 2227.06     9.4 2225.43    54.8 2219.75    73.7 2216.21   115.4  2209.1
   129.6 2207.36   137.9 2206.71   175.7 2205.12   183.3 2205.17   209.8 2204.41
   258.9 2202.11   296.7 2201.58   305.1 2200.92   372.3 2198.94   386.9  2197.4
   391.2 2197.64   410.1 2197.47   448.82196.788   459.3 2196.75  468.882196.875
   504.4 2197.81   544.2 2197.22   548.1 2197.64   555.4 2199.61   566.4 2200.36
   577.2 2201.93   590.8 2202.52   613.7 2202.92   639.2  2202.9     667 2205.22
#Mann= 4 ,-1 , 0
       0      .1       0  181.67     .05       0   448.8    .045       0
  468.88     .05       0
#XS Ineff= 2 , 0
          392.98 2198.61  501.92         2199.13
Permanent Ineff=
       F       F
Bank Sta=448.8,468.88
XS Rating Curve= 0 ,0
Exp/Cntr=0.3,0.1

Type RM Length L Ch R = 1 ,1597    ,91.7,84.4,78.4
XS GIS Cut Line= 3
2112412.44419235360984.6811193282111929.61104565360710.948941675
2111626.41464054360749.917758633
#Sta/Elev= 30
       0 2251.27    70.6 2242.87   134.9 2233.95   153.6 2231.94   191.3 2224.59
     224 2216.16   243.2 2210.38   268.3  2206.2     301 2203.99   345.9 2203.68
   361.2 2202.15   372.3 2199.45   381.4 2198.23   413.8 2196.62   459.1 2196.57
   474.6 2195.97     527 2196.79   534.6 2196.39   541.7 2195.74   545.8 2196.35
   556.9 2197.29   583.3 2197.59   606.8 2198.98   652.8 2199.37   672.6 2200.16
   702.4 2202.58   718.9 2202.86   765.3 2201.99   824.8 2205.68   860.7  2206.1
#Mann= 4 ,-1 , 0
       0      .1       0   413.8     .05       0   534.6    .045       0
   545.8     .05       0
#XS Ineff= 2 , 0
          458.12 2198.52
Permanent Ineff=
       F       F
Bank Sta=534.6,545.8
XS Rating Curve= 0 ,0
Exp/Cntr(USF)=0,0
Exp/Cntr=0.5,0.3

Type RM Length L Ch R = 1 ,1512    ,39.7,39.3,38.7
XS GIS Cut Line= 4
2112257.35512081360685.5729828032112092.11168489 360627.69383347
2111949.40330888360657.9024344832111585.86171314360730.818955317
#Sta/Elev= 30
       0 2209.62    14.5 2207.72    29.4 2206.36    46.8 2205.39    57.2 2204.29
    81.4 2203.47   119.8 2203.03   130.2 2202.05   143.2 2200.13   161.2 2198.99
   192.1 2197.94   225.7 2197.43   235.7 2196.47   248.6 2195.91   273.5 2195.44
   282.7 2195.12  291.042195.412   306.2 2195.38   319.6    2197   329.6 2197.58
   349.7 2197.37   416.6 2198.65   436.7  2199.8   468.8 2202.77   480.2 2203.38
   537.1 2204.72   560.5  2204.3     594 2205.34   670.9 2205.97   691.7 2206.47
#Mann= 4 ,-1 , 0
       0      .1       0    14.5     .05       0   273.5    .045       0
  291.04     .05       0
#XS Ineff= 2 , 0
           268.5  2196.8  296.04          2196.8
Permanent Ineff=
       F       F
Bank Sta=273.5,291.04
XS Rating Curve= 0 ,0
Exp/Cntr=0.5,0.3

Type RM Length L Ch R = 1 ,1473    ,121.5,121.1,125
XS GIS Cut Line= 4
2112278.18874055360645.9897286442112084.81970473360581.860591814
2111918.15337139360628.7354980562111573.36173813360704.777340725
#Sta/Elev= 30
       0 2209.97    15.3 2207.73      27 2206.69    54.3 2205.34    75.4  2203.8
   116.8 2202.77   137.6 2203.07   158.3 2200.97   172.1 2200.08   181.5 2200.14
   192.9 2201.07   220.5 2199.72   249.8 2199.42   288.5  2197.4  308.262194.488
   312.3 2194.19  328.342194.479   353.2 2195.13   363.4 2196.51   366.8 2196.69
   421.5 2197.64   473.8 2199.75   490.3 2201.44   508.1 2202.18   521.5 2203.12
   565.2 2203.49   574.7    2204   622.1 2204.58     639 2205.59   729.9 2205.53
#Mann= 4 ,-1 , 0
       0      .1       0    15.3     .05       0  308.26    .045       0
  328.34     .05       0
Bank Sta=308.26,328.34
XS Rating Curve= 0 ,0
Exp/Cntr=0.5,0.3

Type RM Length L Ch R = 1 ,1352    ,97.1,101.8,113.5
XS GIS Cut Line= 5
2112284.43872805360637.6564119762112057.35519272360558.489575565
2111967.77203855360499.114694312 2111815.6886813360519.947985977
2111603.18845014360526.197973475
#Sta/Elev= 30
       0 2210.13    19.8 2207.52    52.2 2205.64    75.4 2203.78   125.2 2202.61
   134.7 2203.13     163 2201.21   187.5 2201.29   222.3 2200.45   242.4 2199.74
     266 2198.18   308.4 2197.56     333 2196.22   356.3 2196.77   362.1 2196.15
   375.1 2193.83   381.7 2193.36   391.2 2193.38   404.9 2193.16   414.5 2193.45
   421.4 2194.18   431.4 2196.46   434.7 2196.81   447.9 2196.47     491 2196.38
     514 2197.38   543.8 2200.39   550.1 2200.75   629.5 2200.26   714.1 2202.28
#Mann= 4 ,-1 , 0
       0      .1       0    19.8     .05       0   391.2    .045       0
   414.5     .05       0
Bank Sta=391.2,414.5
XS Rating Curve= 0 ,0
Exp/Cntr=0.5,0.3

Type RM Length L Ch R = 1 ,1250    ,41,42.6,41.6
XS GIS Cut Line= 5
2112281.31373431360626.1981015652112092.11168489360556.860641807
2111917.11170681360392.2773095672111850.44484539360331.860763729
2111809.81992663 360311.02714397
#Sta/Elev= 30
       0  2208.9     9.8 2207.84    40.5 2205.95    58.4 2204.29      66 2203.89
   117.2  2202.7   132.5 2202.85     199 2201.16   215.4 2200.26     241 2197.31
   260.4 2196.02     292 2195.77     299 2195.43   314.5 2195.51   340.1  2194.2
     373 2194.32   386.6 2195.06   401.2 2192.81   410.4 2192.48   417.4 2192.87
   424.4 2194.33     429 2194.88   436.1 2195.16   449.5  2194.8   458.3  2195.3
   477.8 2195.76   489.3 2196.62   503.3 2198.11   512.6 2198.68   577.4 2199.31
#Mann= 4 ,-1 , 0
       0      .1       0     9.8     .05       0   401.2    .045       0
   417.4     .05       0
#XS Ineff= 2 , 0
           386.2  2195.8   431.4          2195.8
Permanent Ineff=
       F       F
Bank Sta=401.2,417.4
XS Rating Curve= 0 ,0
Exp/Cntr=0.5,0.3

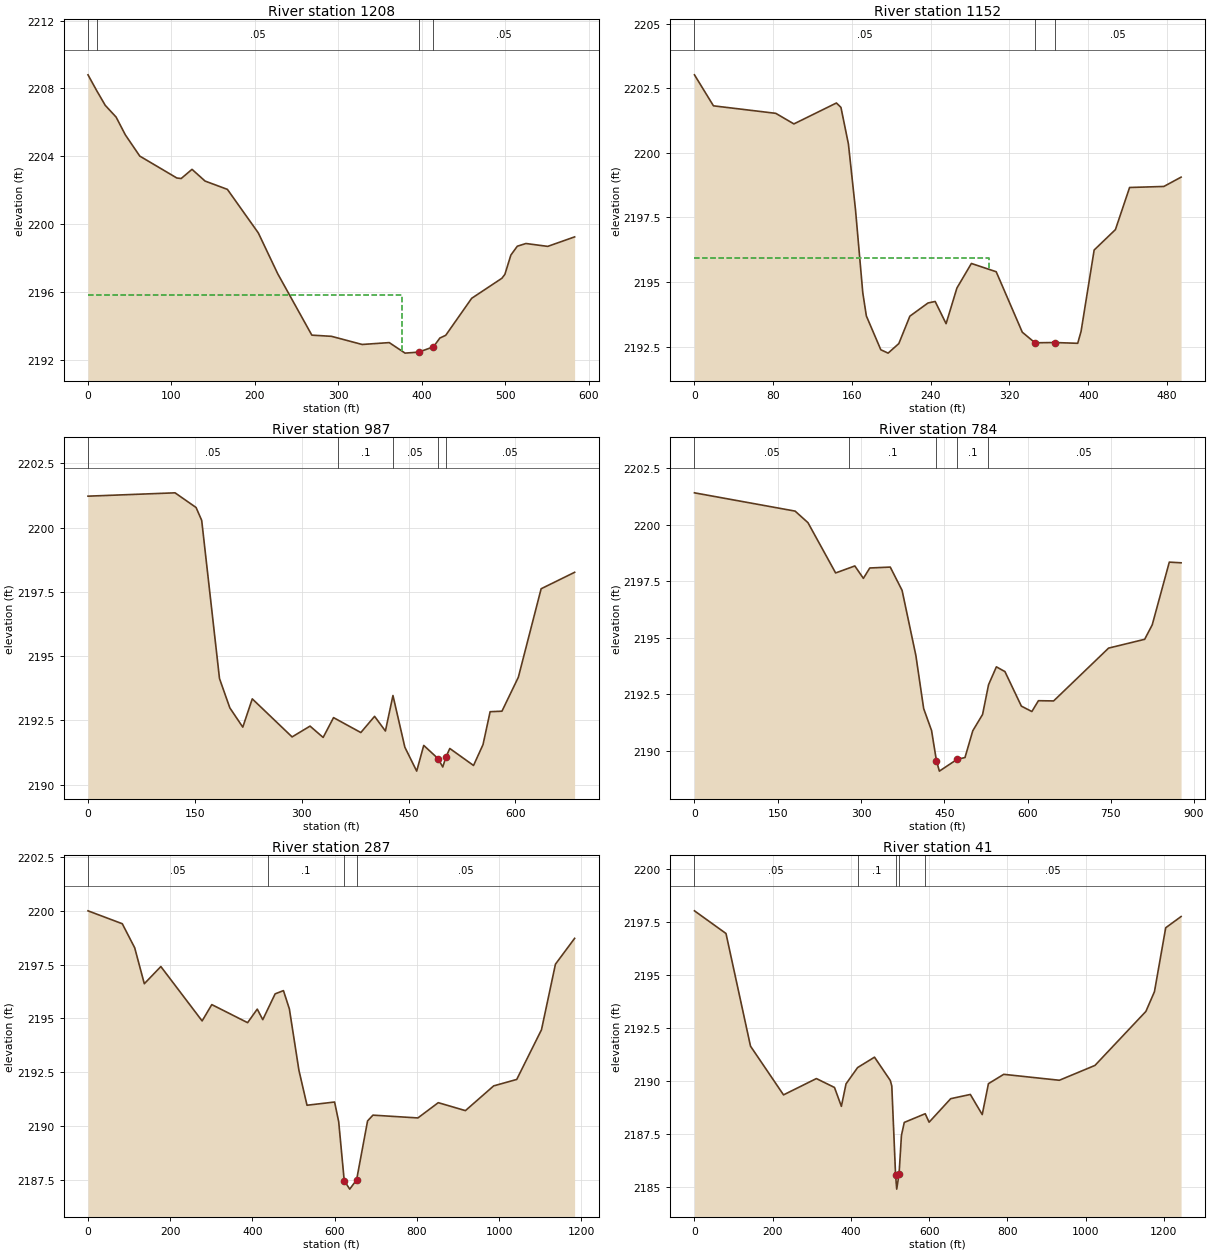
Type RM Length L Ch R = 1 ,1208    ,66.1,55.7,53.8
XS GIS Cut Line= 5
2112288.60538639360609.5314682282112148.02299039360563.449211314
2112000.10629147360415.5325123972111935.52308731360351.990972817
2111812.60633838360294.699092641
#Sta/Elev= 30
       0  2208.8    10.3 2207.88    20.7    2207    33.7 2206.31    44.8 2205.26
    62.1 2204.01   106.5 2202.72   111.7 2202.69   124.7 2203.23   140.3 2202.54
   167.1 2202.05   204.2 2199.48   227.4 2197.08   268.3 2193.46   291.9 2193.39
   328.6 2192.91   361.1 2193.02   380.1  2192.4   396.3 2192.46  414.052192.769
   421.8 2193.29   428.8 2193.45   459.9 2195.63   496.1 2196.81   499.7 2197.04
   506.9 2198.18   514.6  2198.7     525 2198.86   551.1 2198.69   583.3 2199.25
#Mann= 4 ,-1 , 0
       0      .1       0    10.3     .05       0   396.3    .045       0
  414.05     .05       0
#XS Ineff= 2 , 0
           376.3  2195.8
Permanent Ineff=
       F       F
Bank Sta=396.3,414.05
XS Rating Curve= 0 ,0
Exp/Cntr=0.5,0.3

Type RM Length L Ch R = 1 ,1152    ,166.4,164.7,165.3
XS GIS Cut Line= 4
2112276.98446974360454.2547664742112009.06910086360317.987466786
2111906.14834178360332.9527111762111824.32005928360296.129984051
#Sta/Elev= 30
       0 2203.02    19.3 2201.82    82.6 2201.53     101 2201.12   144.2 2201.93
   148.8 2201.76   156.4 2200.34   163.6 2197.79     171 2194.58   174.6 2193.69
   189.3 2192.38   196.7 2192.25   207.6 2192.62   218.8 2193.68   237.2 2194.19
   244.5 2194.25   255.6 2193.39   266.6 2194.77   281.3 2195.72   306.5  2195.4
     333 2193.06   345.9 2192.65   366.1 2192.66   389.3 2192.63   392.7 2193.09
     406 2196.24   427.6 2197.03     442 2198.66   476.8  2198.7   494.3 2199.06
#Mann= 3 ,-1 , 0
       0     .05       0   345.9    .045       0   366.1     .05       0
#XS Ineff= 2 , 0
          299.66 2195.92
Permanent Ineff=
       F       F
Bank Sta=345.9,366.1
XS Rating Curve= 0 ,0
Exp/Cntr(USF)=0,0
Exp/Cntr=0.3,0.1

Type RM Length L Ch R = 1 ,987     ,202,203.6,196.3
XS GIS Cut Line= 5
2112310.30678655360393.8137238172112186.17481697  360325.2374174
2111930.96633789360202.8416648062111777.32064781 360176.79972215
2111674.89007838360177.667830646
#Sta/Elev= 30
       0 2201.22   122.2 2201.35   151.7 2200.78   159.6 2200.28   184.6 2194.13
   199.1 2192.99   217.3 2192.24   230.6 2193.34   286.5 2191.86   311.7 2192.28
   330.1 2191.84   344.7 2192.61     383 2192.03   402.3 2192.66   417.5 2192.09
   428.1 2193.47   444.8 2191.46   461.4 2190.53   471.3 2191.53   491.3 2191.02
     498 2190.69  502.44 2191.08   507.9 2191.41   541.2 2190.75   554.5 2191.56
   564.5 2192.84   581.1 2192.86   604.1 2194.18   636.1 2197.62   683.1 2198.26
#Mann= 5 ,-1 , 0
       0     .05       0  351.11      .1       0  427.53     .05       0
   491.3    .045       0  502.44     .05       0
Bank Sta=491.3,502.44
XS Rating Curve= 0 ,0
Exp/Cntr=0.3,0.1

Type RM Length L Ch R = 1 ,784     ,463.7,496.9,446.5
XS GIS Cut Line= 4
2112361.52190723360255.7930024712112075.06349064360081.313692644
2111867.59835438359997.1124174742111562.91097164360085.653907061
#Sta/Elev= 30
       0 2201.42   181.3 2200.61   204.4  2200.1   254.3 2197.87   288.9 2198.18
   304.3 2197.63   315.8 2198.09   352.7 2198.13     374  2197.1   398.8 2194.22
   412.9 2191.86   427.1 2190.89   435.9 2189.55   441.2 2189.09   473.6 2189.62
   487.3 2189.69   501.4 2190.88     519  2191.6   529.8 2192.92   543.9 2193.71
   559.3  2193.5   588.9 2191.97   607.8 2191.73   619.6 2192.21     647  2192.2
     746 2194.54     811 2194.93   824.6 2195.57   855.4 2198.35   876.6 2198.32
#Mann= 5 ,-1 , 0
       0     .05       0  277.82      .1       0   435.9    .045       0
   473.6      .1       0   527.9     .05       0
Bank Sta=435.9,473.6
XS Rating Curve= 0 ,0
Exp/Cntr=0.3,0.1

Type RM Length L Ch R = 1 ,287     ,245.4,245.4,245.4
XS GIS Cut Line= 5
2112603.36230281359910.8274850552112163.08431198359820.549778476
2112036.69545713359791.3831701432111889.47331063359819.161001727
2111517.25095797360080.272028059
#Sta/Elev= 30
       0    2200    83.4  2199.4   113.6 2198.28     137 2196.61   177.2 2197.41
   277.6 2194.88   301.1 2195.64   388.2  2194.8   411.7 2195.43   425.1 2194.94
   455.2 2196.14   475.4 2196.29   489.8 2195.44     513 2192.59   532.7 2190.96
   599.8 2191.11   609.8 2190.19   623.2 2187.46   636.6 2187.06   653.3 2187.49
     680 2190.23   693.1  2190.5   802.4 2190.37     852 2191.08     918 2190.71
   986.7 2191.86  1042.8 2192.16    1103 2194.47    1137 2197.52  1183.6 2198.72
#Mann= 4 ,-1 , 0
       0     .05       0  437.79      .1       0   623.2    .045       0
   653.3     .05       0
Bank Sta=623.2,653.3
XS Rating Curve= 0 ,0
Exp/Cntr=0.3,0.1

Type RM Length L Ch R = 1 ,41      ,,,
XS GIS Cut Line= 4
2112604.96916997359668.9584572092112114.31402993359613.046003909
2112069.70149915359637.1608854092111512.64773649360060.377055744
#Sta/Elev= 30
       0 2198.02    80.6 2196.95   143.3 2191.63   227.7 2189.33   311.7  2190.1
     358 2189.68   375.6 2188.79   387.5 2189.85   417.1 2190.62   460.3 2191.11
   500.7 2190.01   504.5 2189.75   514.22185.535   517.1 2184.88   523.1  2185.6
   529.2 2187.42   536.4 2188.03     590 2188.44   599.9 2188.04   655.1 2189.15
   705.3 2189.35   735.7  2188.4   751.6 2189.86   790.7  2190.3   932.9 2190.02
  1023.9 2190.72  1154.1 2193.27    1176  2194.2  1204.8 2197.22  1244.1 2197.75
#Mann= 5 ,-1 , 0
       0     .05       0   417.1      .1       0   514.2    .045       0
   523.1      .1       0     590     .05       0
Bank Sta=514.2,523.1
XS Rating Curve= 0 ,0
Exp/Cntr(USF)=0,0
Exp/Cntr=0.3,0.1
LCMann Table=0

Chan Stop Cuts=-1
Use User Specified Reach Order=0
Composite Channel Slope=5